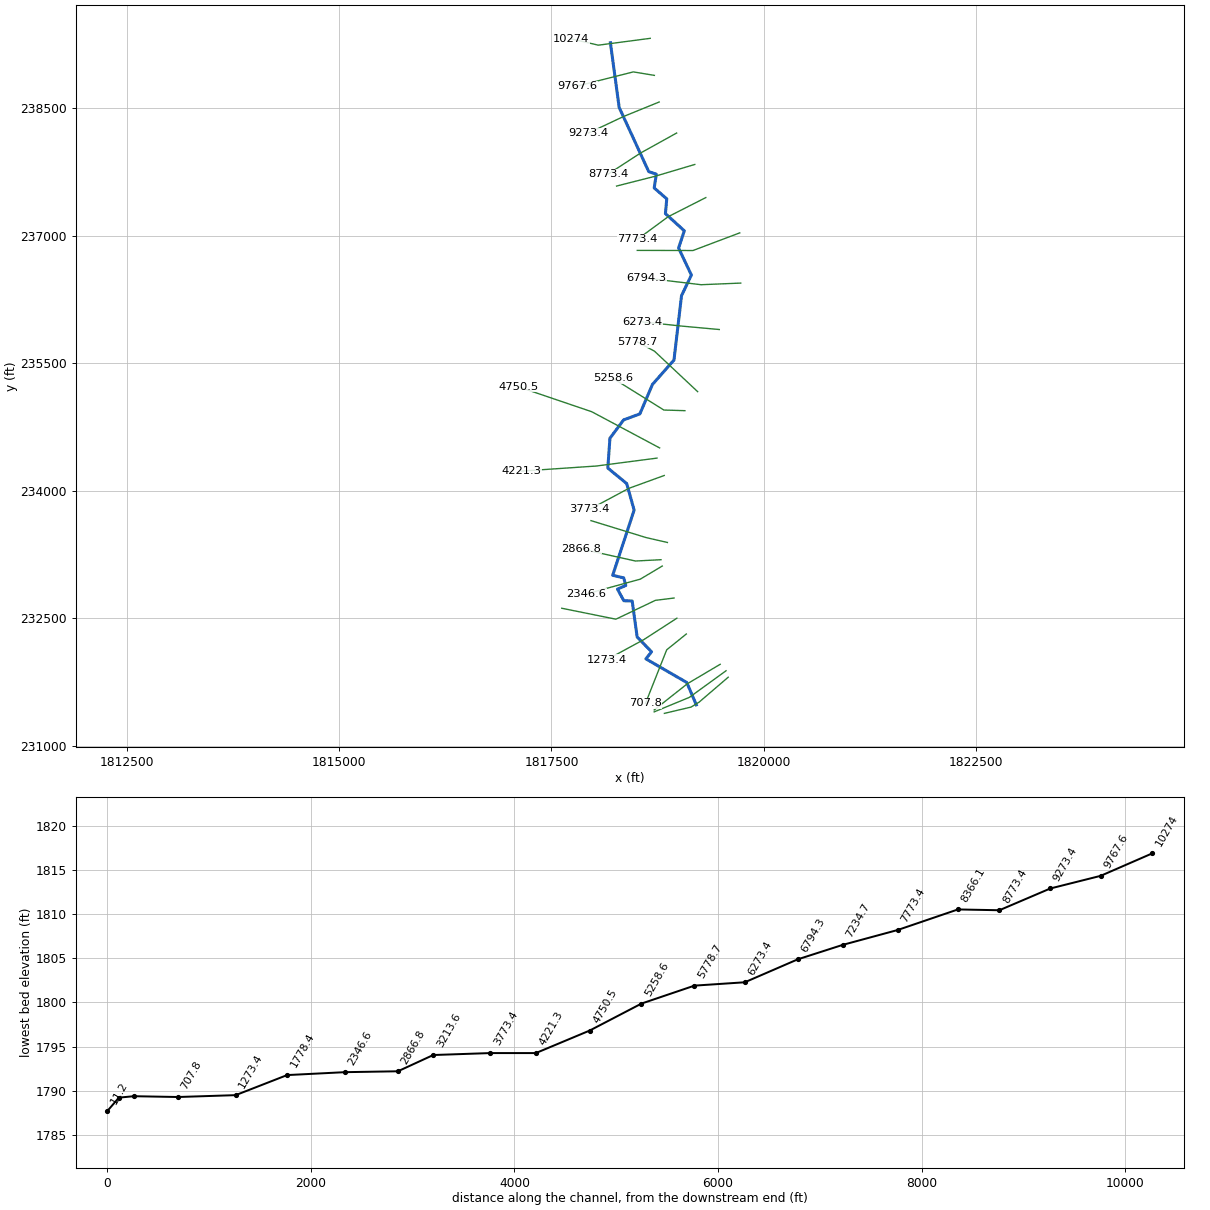
--- LtFkRkCaCr.prj (project) ---

Proj Title=LtFkRkCaCr
Current Plan=p01
Default Exp/Contr=0,0
English Units
Geom File=g01
Flow File=f01
Plan File=p01
BEGIN DESCRIPTION:
END DESCRIPTION:
DSS Export Rating Curves= 0
DSS Export Rating Curve Sorted= 0
DSS Export Volume Flow Curves= 0
DXF OffsetX= 0
DXF OffsetY= 0
DXF ScaleX= 0
DXF ScaleY= 0

--- LtFkRkCaCr.p01 (plan) ---

Plan Title=Floodplain
Program Version=4.00
Geom File=g01
Flow File=f01
K Sum by GR=0
Std Step Tol=0.01
Critical Tol=0.01
Num of Std Step Trials=20
Max Error Tol=0.3
Flow Tol Ratio=0.001
Split Flow NTrial=30
Split Flow Tol=0.02
Split Flow Ratio=0.02
Log Output Level=0
Friction Slope Method=1
Unsteady Friction Slope Method=2
Unsteady Bridges Friction Slope Method=1
Global Log Level=0
CheckData=False
Run HTab=0
Run UNet=0
Run PostProcess=0
UNET Theta=0
UNET Theta Warmup=0
UNET ZTol=0
UNET ZSATol=0
UNET MxIter=0
UNET MaxInSteps=0
UNET DtIC=0
UNET DtMin=0
UNET MaxCRTS=0
UNET WFStab=0
UNET SFStab=0
UNET WFX=0
UNET SFX=0
UNET DSS MLevel=0
UNET DZMax Abort=0
UNET Convert EG Bridges=0
UNET Use Existing IB Tables=0
UNET Froude Limit=0
UNET Froude Power=0
Write IC File=0
Echo Input=False
Echo Output=False
Write Detailed=0

--- LtFkRkCaCr.f01 (steady flow) ---

Flow Title=NFF Regression Equation
Program Version=4.00
Number of Profiles=1
Profile Names=P100yr
River Rch & RM=LtFkRkCaCr,Main      ,10274
633.9796
River Rch & RM=LtFkRkCaCr,Main      ,8773.4
682.8635
River Rch & RM=LtFkRkCaCr,Main      ,6794.3
715.3998
River Rch & RM=LtFkRkCaCr,Main      ,6794.3
833.5066
River Rch & RM=LtFkRkCaCr,Main      ,4750.5
863.3833
River Rch & RM=LtFkRkCaCr,Main      ,4221.3
934.6596
River Rch & RM=LtFkRkCaCr,Main      ,3773.4
1021.528
River Rch & RM=LtFkRkCaCr,Main      ,126.8
1109.936
Boundary for River Rch & Prof#=LtFkRkCaCr,Main      ,1
Up Type=0
Dn Type=3
Dn Slope=0.004728

--- LtFkRkCaCr.g01 (geometry) ---

Geom Title=USGS 10m DEM
Program Version=4.00

River Reach=LtFkRkCaCr      ,Main
Reach XY= 30
     1818194.058       239271.89     1818297.303      238510.815
     1818644.916      237755.757      1818734.78      237725.288
     1818709.375      237563.711     1818857.233      237435.161
     1818841.482      237261.898     1819063.523      237059.165
     1818996.453      236856.432     1819147.343      236538.295
     1819031.004      236295.994     1818942.086      235537.905
     1818689.051      235251.335     1818540.685        234904.3
      1818349.13      234833.674     1818188.569       234617.73
     1818163.672      234267.139     1818386.221      234084.222
     1818473.107      233772.247     1818221.088      233005.011
     1818350.654      232974.525     1818375.043      232885.607
     1818277.487      232842.419      1818351.83      232705.757
     1818450.242       232702.69     1818508.674      232279.441
     1818678.381      232105.161     1818611.311      232021.832
     1819092.993      231743.392     1819205.102      231480.033

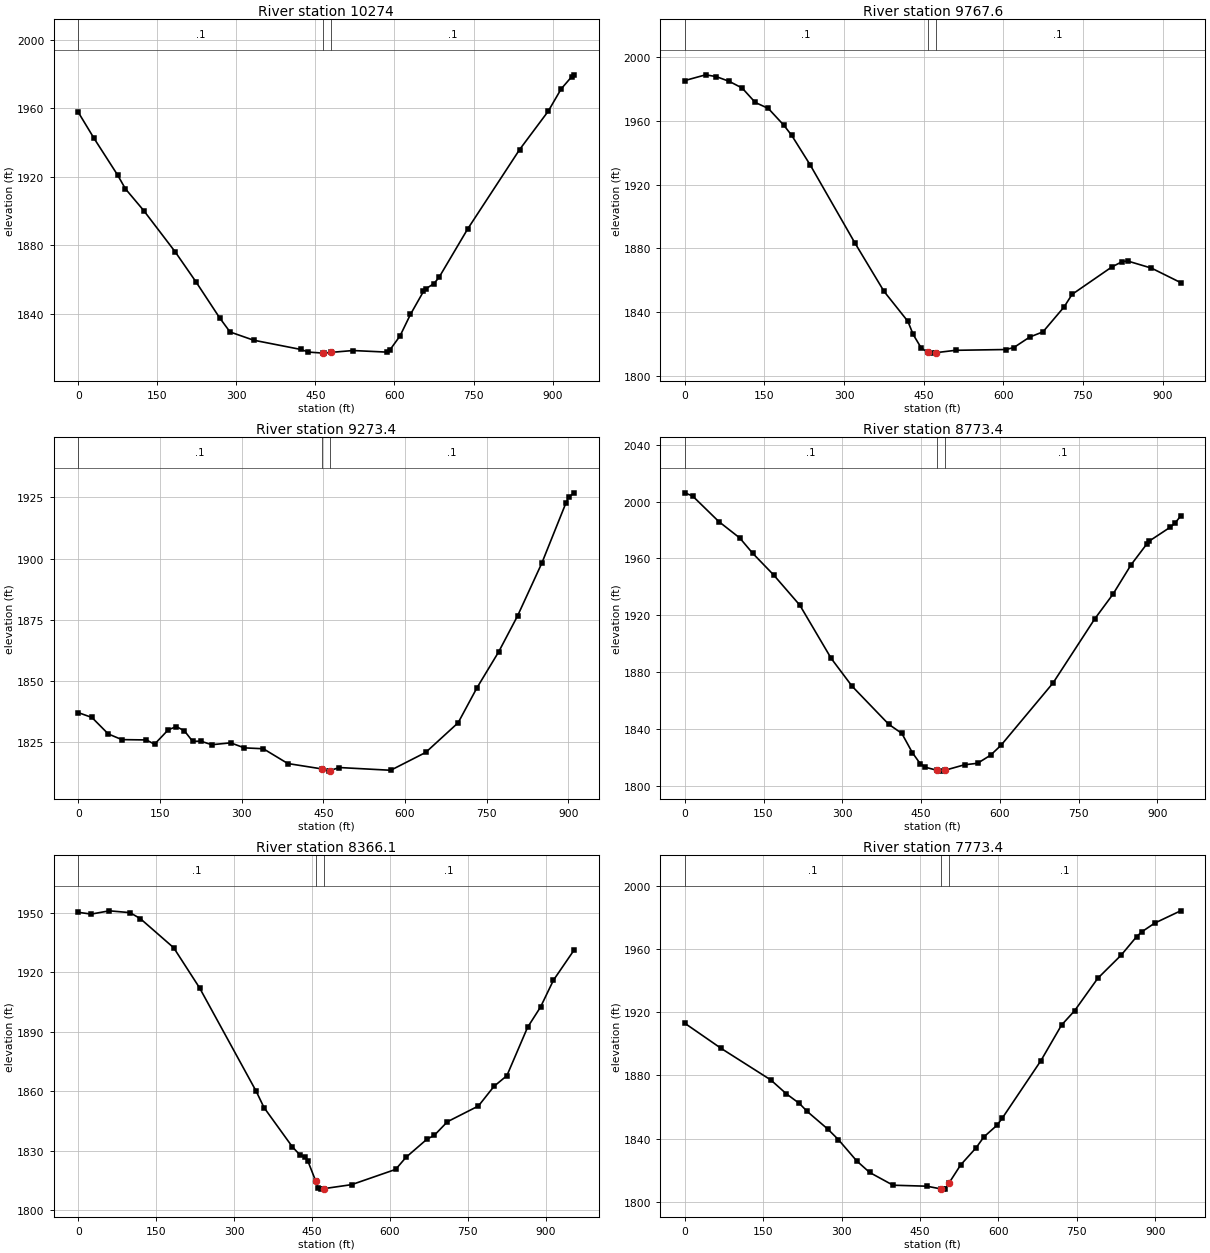
Type RM Length L Ch R = 1 ,10274   ,453.8,506.4,512.8
XS GIS Cut Line= 3
     1818662.721      239324.223      1818052.51      239243.735
     1817735.417      239317.459
#Sta/Elev= 30
       0 1957.71    29.8 1942.52    74.5 1921.06    89.4 1912.96   124.1 1900.26
   183.7 1876.16   223.4 1858.49     268 1837.58   287.9 1829.23   332.6 1824.42
   421.9 1819.02   436.8 1817.46   464.5 1816.86   466.6 1816.85   479.5 1817.28
   521.2 1818.37   585.7 1817.44   590.7 1818.46   610.5 1826.89   630.3 1839.49
     655 1852.94   659.9 1854.56   674.7 1857.48   684.6 1861.18   738.8 1889.44
   837.5 1935.96   891.7 1958.34   916.4 1971.46   936.1 1978.49     941 1979.67
#Mann= 3 , 0 , 0
       0      .1       0   464.5    .045       0   479.5      .1       0
Bank Sta=464.5,479.5
XS Rating Curve= 0 ,0
Exp/Cntr=0.3,0.1

Type RM Length L Ch R = 1 ,9767.6  ,490.9,494.2,501.2
XS GIS Cut Line= 3
     1818711.606       238888.38     1818464.309      238929.271
     1817801.599      238762.116
#Sta/Elev= 30
       0 1985.43    39.3 1989.02      59 1987.93    83.6 1984.94   108.1 1980.72
   132.7 1971.68   157.3 1967.93   186.8 1957.29   201.5 1950.95   235.9 1932.64
   320.5 1883.44   375.4 1853.05   420.3 1834.25   430.2 1826.04   445.2 1817.65
   457.6 1814.74   465.2 1814.31   472.6 1814.57   510.1 1816.08   604.9 1816.57
   619.8  1817.8   649.8 1824.41   674.7 1827.64   714.6 1843.32   729.6 1851.19
   804.4 1868.38   824.4 1871.82   834.4 1872.13   879.2 1867.67   934.1  1858.6
#Mann= 3 , 0 , 0
       0      .1       0   457.6    .045       0   472.6      .1       0
Bank Sta=457.6,472.6
XS Rating Curve= 0 ,0
Exp/Cntr=0.3,0.1

Type RM Length L Ch R = 1 ,9273.4  ,501.4,500,502.3
XS GIS Cut Line= 3
     1818768.233      238575.072     1818346.913      238403.503
     1817934.426      238208.964
#Sta/Elev= 30
       0 1836.85      25 1834.86      55 1828.11      80 1825.79     125 1825.66
     140  1823.9     165 1829.76     180 1831.15     195 1829.36     210 1825.08
     225 1825.17     245  1823.7     280 1824.47   304.9 1822.41   339.9 1822.05
   384.9 1815.99   447.4 1813.79   459.9 1812.88   462.4 1813.13   479.7 1814.35
   573.9 1813.23   638.3 1820.55   697.8 1832.69   732.5 1847.06   772.2 1861.71
   806.9 1876.43   851.5 1898.06   896.1 1922.87   901.1 1925.15     911 1926.91
#Mann= 3 , 0 , 0
       0      .1       0   447.4    .045       0   462.4      .1       0
Bank Sta=447.4,462.4
XS Rating Curve= 0 ,0
Exp/Cntr=0.3,0.1

Type RM Length L Ch R = 1 ,8773.4  ,407.7,407.2,399.9
XS GIS Cut Line= 3
     1818973.647      238210.007     1818546.866      237973.277
     1818164.488      237724.351
#Sta/Elev= 30
       0 2006.18    14.9 2003.93    64.7 1985.99   104.6 1974.45   129.5 1963.58
   169.3 1948.39   219.1 1927.13   278.9 1889.66   318.7  1870.1   388.4 1843.37
   413.3 1836.97   433.3 1823.47   448.2 1815.72   458.2 1813.16   480.5 1810.99
     488 1810.42   495.5 1811.03   532.7 1814.89   557.5 1815.93   582.3 1821.63
   602.1 1828.54   701.3 1872.42   780.6 1917.44   815.4 1934.84   850.1 1955.66
   879.8 1970.16   884.8 1972.31   924.5 1981.98   934.4 1985.25   944.3 1989.83
#Mann= 3 , 0 , 0
       0      .1       0   480.5    .045       0   495.5      .1       0
Bank Sta=480.5,495.5
XS Rating Curve= 0 ,0
Exp/Cntr=0.3,0.1

Type RM Length L Ch R = 1 ,8366.1  ,593,592.8,620.4
XS GIS Cut Line= 3
     1819186.615      237839.664     1818715.553      237699.762
     1818266.703      237585.851
#Sta/Elev= 30
       0 1950.28    24.8 1949.38    59.6 1951.03    99.3 1950.12   119.1 1947.14
   183.6 1932.38   233.3 1912.17   342.5 1859.86   357.4 1851.72     412 1831.87
   426.9 1827.69   436.8 1826.69   441.8 1824.76   457.1  1814.5   461.6 1811.26
   466.6 1810.51   472.1 1810.73   526.2 1812.78   610.9 1820.48   630.8 1826.58
   670.6 1835.61   685.6 1837.77   710.5 1844.54   770.2 1852.49   800.1 1862.39
     825  1867.8   864.8 1892.19   889.8 1902.46   914.6 1915.99   954.5 1931.29
#Mann= 3 , 0 , 0
       0      .1       0   457.1    .045       0   472.1      .1       0
Bank Sta=457.1,472.1
XS Rating Curve= 0 ,0
Exp/Cntr=0.3,0.1

Type RM Length L Ch R = 1 ,7773.4  ,550,538.7,523.5
XS GIS Cut Line= 3
     1819317.135      237450.229     1818873.134      237224.592
     1818510.405      236957.414
#Sta/Elev= 30
       0 1912.99    69.7 1897.07   164.4  1877.2   194.2 1868.43   219.1 1862.35
   234.1 1857.29   273.9 1846.02   293.8 1839.48   328.7 1826.08   353.6 1818.73
   398.4 1810.65   463.2 1810.03   490.5 1808.28   493.1 1808.18     498 1808.32
   505.5 1812.03   527.8 1823.49   557.4 1834.34   572.3  1841.2   597.1 1848.49
     607 1852.84   681.2  1889.3   720.8 1911.86   745.6 1920.83   790.1  1941.4
   834.7 1955.98   864.4 1967.71   874.3 1970.77     899 1976.26   948.6 1984.03
#Mann= 3 , 0 , 0
       0      .1       0   490.5    .045       0   505.5      .1       0
Bank Sta=490.5,505.5
XS Rating Curve= 0 ,0
Exp/Cntr=0.3,0.1

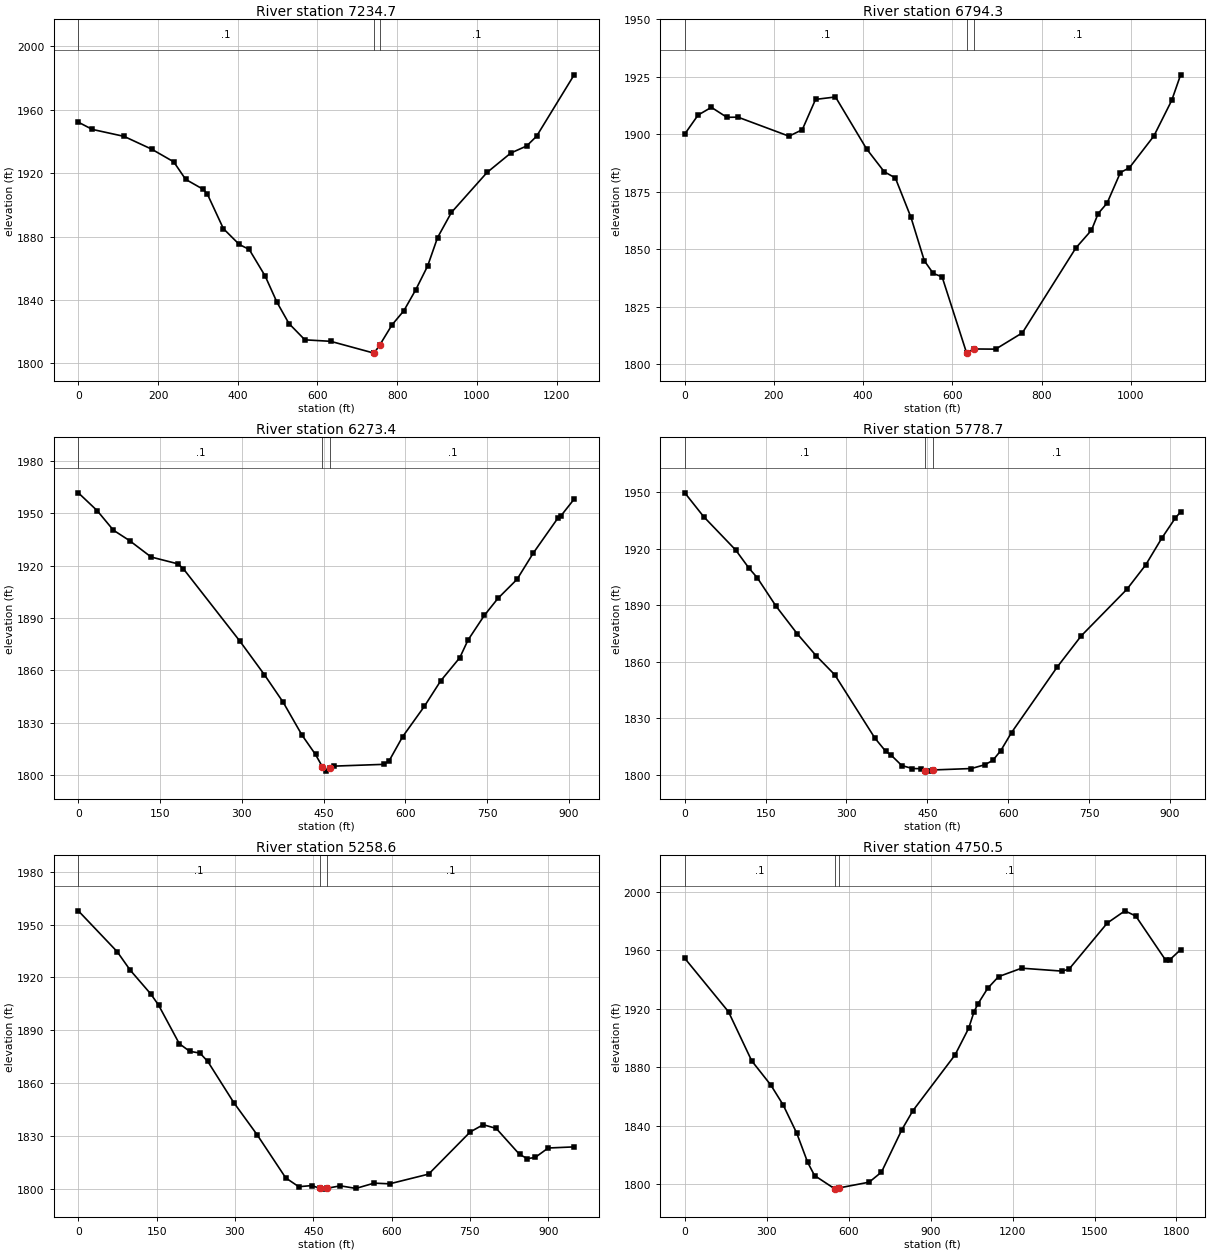
Type RM Length L Ch R = 1 ,7234.7  ,441,440.4,437.9
XS GIS Cut Line= 3
     1819716.552      237034.995     1819166.239      236827.224
     1818510.591      236828.591
#Sta/Elev= 30
       0 1952.13    34.9 1947.58   114.6 1943.19   184.4 1935.06   239.3 1927.12
   269.2 1916.08     314 1909.69     324 1906.63   363.9 1884.99   403.8 1875.01
   428.7 1871.88   468.6 1855.16   498.5  1838.5   528.4 1825.16   568.3 1814.89
   632.9 1813.95   741.4 1806.52   742.2  1806.5   756.4  1811.7   786.9  1824.3
   816.7 1833.25   846.5 1846.47   876.3 1861.43   901.2 1879.35   935.9 1895.18
  1025.3 1920.41  1084.9 1932.66  1124.7 1937.12  1149.5 1943.22  1243.9 1981.99
#Mann= 3 , 0 , 0
       0      .1       0   741.4    .045       0   756.4      .1       0
Bank Sta=741.4,756.4
XS Rating Curve= 0 ,0
Exp/Cntr=0.3,0.1

Type RM Length L Ch R = 1 ,6794.3  ,521.2,520.9,521
XS GIS Cut Line= 3
     1819728.407      236444.022     1819261.702      236424.784
     1818621.577      236501.331
#Sta/Elev= 30
       0 1900.11    29.8 1908.34    59.6 1911.69    94.4 1907.35   119.3 1907.42
   233.6 1899.16   263.4 1901.96   293.2 1915.14   337.9  1916.2   407.5 1893.66
   447.2 1883.69   472.1 1881.01   507.1  1863.9   537.1 1845.01   557.1 1839.51
     577    1838     632 1804.87   633.6 1805.02   648.6 1806.68     697  1806.6
     757  1813.7   876.9 1850.59   911.9  1858.3   926.9 1865.53   946.9 1870.06
   976.8 1883.37   996.8  1885.4  1051.8 1899.23  1091.8  1914.7  1111.8 1925.82
#Mann= 3 , 0 , 0
       0      .1       0   633.6    .045       0   648.6      .1       0
Bank Sta=633.6,648.6
XS Rating Curve= 0 ,0
Exp/Cntr=0.3,0.1

Type RM Length L Ch R = 1 ,6273.4  ,510.1,494.7,479.5
XS GIS Cut Line= 3
     1819475.294      235897.416     1819022.121      235938.881
     1818569.722      235987.351
#Sta/Elev= 30
       0 1961.77    34.6 1951.55    64.3 1940.37      94 1934.38   133.6 1924.98
     183 1921.04   192.9 1918.19   296.8 1876.63   341.3 1857.62   375.9 1841.77
   410.6 1822.86   435.3 1811.81   447.6 1804.92   455.1 1802.27   462.6 1804.02
   470.1 1805.15   560.1 1806.15   570.1 1807.99   595.1 1821.96   635.1 1839.41
   665.1 1854.03   700.1 1867.28   715.1 1877.35   745.1  1891.5   770.1 1901.27
   805.1 1912.18   835.1  1927.3   880.1 1947.28   885.1 1948.34     910 1958.18
#Mann= 3 , 0 , 0
       0      .1       0   447.6    .045       0   462.6      .1       0
Bank Sta=447.6,462.6
XS Rating Curve= 0 ,0
Exp/Cntr=0.3,0.1

Type RM Length L Ch R = 1 ,5778.7  ,514.4,520.1,525.9
XS GIS Cut Line= 3
     1819221.013      235166.107     1818713.468      235642.054
     1818516.227      235748.648
#Sta/Elev= 30
       0  1949.6    34.8 1937.02    94.4 1919.25   119.3 1909.53   134.2 1904.63
     169 1889.56   208.7 1874.76   243.5  1863.2   278.3 1853.01   352.9 1819.34
   372.8  1812.4   382.7 1810.41   402.6 1804.85   422.4 1803.27   437.4 1803.18
   446.3 1802.08   452.3 1801.89   461.3 1802.52   531.8 1803.27   556.6 1805.27
   571.5 1807.57   586.4 1812.82   606.3 1822.38   690.8 1857.07   735.6 1873.69
   820.4 1898.44   855.2 1911.34   885.1 1925.56     910 1936.16     920 1939.51
#Mann= 3 , 0 , 0
       0      .1       0   446.3    .045       0   461.3      .1       0
Bank Sta=446.3,461.3
XS Rating Curve= 0 ,0
Exp/Cntr=0.3,0.1

Type RM Length L Ch R = 1 ,5258.6  ,507.1,508.1,508.6
XS GIS Cut Line= 3
     1819071.056      234942.467     1818823.281      234949.898
     1818227.773      235321.061
#Sta/Elev= 30
       0 1957.84    74.4 1934.65    99.2 1924.22   138.8 1910.62   153.7 1904.31
   193.4 1882.41   213.2 1878.11     233 1877.07   247.9 1872.33   297.6 1849.02
   342.4 1830.74   397.2 1806.24   422.1 1801.24     447 1801.87   462.1 1800.37
   471.8 1799.86   477.1 1800.38   501.7 1801.74   531.6 1800.26   566.4 1803.26
   596.2 1802.87   670.9 1808.39   750.5 1832.31   775.4 1836.43   800.3 1834.33
   845.1 1819.54     860 1817.18   874.9 1817.83   899.8  1823.2   949.6 1823.84
#Mann= 3 , 0 , 0
       0      .1       0   462.1    .045       0   477.1      .1       0
Bank Sta=462.1,477.1
XS Rating Curve= 0 ,0
Exp/Cntr=0.3,0.1

Type RM Length L Ch R = 1 ,4750.5  ,515.5,529.2,542.7
XS GIS Cut Line= 3
     1818773.225      234504.162     1817974.726      234929.932
     1817112.859      235222.767
#Sta/Elev= 30
       0 1954.42     160 1917.93     245 1884.42     315 1867.88     360 1854.35
     410 1834.95     450    1815     475  1806.1   548.4 1797.08     550 1796.81
   563.4 1797.58   674.9 1801.56   719.9  1808.4   794.9 1837.48   834.9 1850.34
   989.5  1888.5  1039.2 1906.65  1059.1 1918.05    1074 1923.56  1108.9 1933.97
  1148.6 1941.92  1233.2  1947.7  1382.4 1945.68  1407.3 1947.19  1546.6 1978.51
  1611.2 1986.87    1651 1983.32  1760.5 1953.14  1775.4 1953.41  1815.2 1960.36
#Mann= 3 , 0 , 0
       0      .1       0   548.4    .045       0   563.4      .1       0
Bank Sta=548.4,563.4
XS Rating Curve= 0 ,0
Exp/Cntr=0.3,0.1

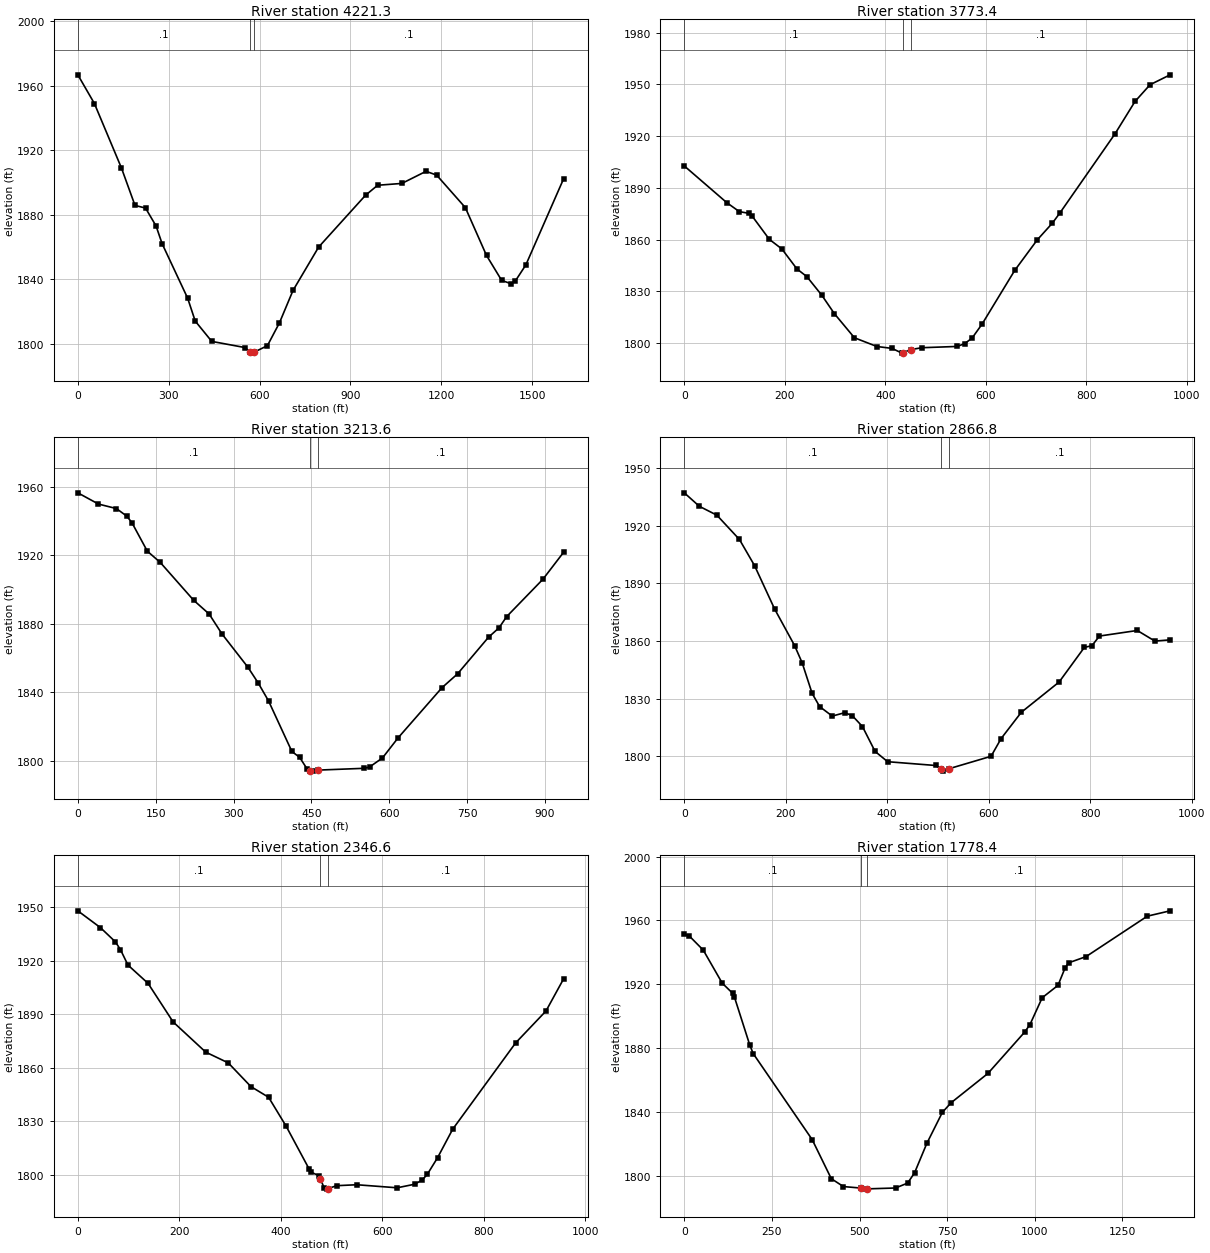
Type RM Length L Ch R = 1 ,4221.3  ,445.8,447.9,456.9
XS GIS Cut Line= 3
     1818742.459      234384.232     1818027.968       234291.02
     1817146.136      234231.122
#Sta/Elev= 30
       0 1966.82    54.7 1949.04   144.1 1909.03   188.8 1885.84   223.6 1884.21
   258.4 1873.08   278.3 1862.14   362.8 1828.28   387.6 1814.16   442.3 1801.53
   551.6 1797.73   567.7 1795.21   576.4 1794.26   582.7 1794.89   626.1 1798.89
   665.9 1813.06   710.6 1833.11   795.4 1860.05   950.2 1892.16   990.2 1898.35
  1070.1 1899.48    1150 1906.99    1185 1904.64  1279.8 1884.48  1349.7 1854.82
  1399.7 1839.37  1429.6 1837.37  1444.6 1838.91  1479.6 1848.95  1604.4 1902.41
#Mann= 3 , 0 , 0
       0      .1       0   567.7    .045       0   582.7      .1       0
Bank Sta=567.7,582.7
XS Rating Curve= 0 ,0
Exp/Cntr=0.3,0.1

Type RM Length L Ch R = 1 ,3773.4  ,574.9,559.7,541.4
XS GIS Cut Line= 3
     1818827.638      234179.741     1818411.379      234028.376
     1817949.696      233781.756
#Sta/Elev= 30
       0 1902.72    84.6 1881.43   109.5 1876.26   129.4 1875.22   134.4  1873.9
   169.2 1860.18   194.1 1854.62     224 1843.07   243.9 1838.56   273.7 1827.74
   298.6 1817.11   338.4 1803.17   383.2 1798.09   413.1 1797.02     433 1794.26
   435.4 1794.49   450.4 1796.32   472.8  1797.4   542.6 1798.13   557.6 1799.74
   572.5 1802.98   592.5 1811.14   657.3 1842.19   702.1 1859.88     732 1869.52
     747  1875.4   856.7 1921.28   896.6 1940.09   926.5 1949.78   966.4 1955.52
#Mann= 3 , 0 , 0
       0      .1       0   435.4    .045       0   450.4      .1       0
Bank Sta=435.4,450.4
XS Rating Curve= 0 ,0
Exp/Cntr=0.3,0.1

Type RM Length L Ch R = 1 ,3213.6  ,346.2,346.9,349.1
XS GIS Cut Line= 3
     1818864.914      233391.294     1818613.638       233449.12
       1817965.4       233648.42
#Sta/Elev= 30
       0 1956.48    39.7 1949.93    74.4 1947.28    94.2  1942.9   104.1 1939.12
   133.9 1922.42   158.7 1915.89   223.1 1893.79   252.9 1885.78   277.8 1874.09
   327.7 1854.68   347.6 1845.46   367.6 1834.93   412.4 1805.52   427.4 1802.06
   442.4    1795     447 1794.11   452.3 1794.04     462 1794.63   552.1 1795.69
     562 1796.43     587 1801.75   616.9 1813.41   701.7 1842.77   731.6 1850.81
   791.4 1872.24   811.4 1877.65   826.3 1884.25   896.1 1906.04     936 1921.81
#Mann= 3 , 0 , 0
       0      .1       0     447    .045       0     462      .1       0
Bank Sta=447,462
XS Rating Curve= 0 ,0
Exp/Cntr=0.3,0.1

Type RM Length L Ch R = 1 ,2866.8  ,497.5,520.2,532.2
XS GIS Cut Line= 3
     1818789.744      233188.698      1818488.71      233173.084
     1817848.408      233315.831
#Sta/Elev= 30
       0 1937.26    29.6 1930.25    64.2 1925.61   108.7 1912.94   138.4 1899.36
   177.9 1876.77   217.4 1857.64   232.3 1848.65     252 1832.67   266.8 1825.84
   291.6 1820.89   316.4 1822.67   331.3 1821.06   351.1 1815.45     376 1802.48
   400.8 1797.11   495.3 1795.14   506.3 1793.21   510.2  1792.2   521.3 1793.42
   604.6 1799.93   624.5  1809.2   664.2 1822.86   738.8 1838.66   788.5 1856.69
   803.4 1857.58   818.3 1862.61   892.8 1865.51   927.6 1859.97   957.5 1860.63
#Mann= 3 , 0 , 0
       0      .1       0   506.3    .045       0   521.3      .1       0
Bank Sta=506.3,521.3
XS Rating Curve= 0 ,0
Exp/Cntr=0.3,0.1

Type RM Length L Ch R = 1 ,2346.6  ,547.3,568.2,575.7
XS GIS Cut Line= 3
     1818804.546      233114.238     1818545.781      232959.625
     1817913.077      232786.278
#Sta/Elev= 30
       0 1947.79    44.5  1938.4    74.1 1930.42      84 1926.08    98.8 1917.45
   138.4 1907.22   187.8 1885.64     252 1868.76   296.5 1862.72   341.2 1849.45
     376 1843.49   410.8 1827.18   455.5 1803.56   460.5 1801.48   475.4  1799.6
   478.1 1797.77   485.3  1792.9   490.3  1792.1   493.1 1792.41   510.2 1794.03
   549.9 1794.55   629.4 1792.85   664.2 1794.86   679.2 1797.31   689.1 1800.52
     709 1809.66   738.8 1825.61     863 1873.94   922.7 1891.75   957.5 1909.76
#Mann= 3 , 0 , 0
       0      .1       0   478.1    .045       0   493.1      .1       0
Bank Sta=478.1,493.1
XS Rating Curve= 0 ,0
Exp/Cntr=0.3,0.1

Type RM Length L Ch R = 1 ,1778.4  ,494.1,505,478.9
XS GIS Cut Line= 4
     1818943.004      232737.382     1818723.451      232710.377
     1818258.643      232488.519     1817621.993      232617.202
#Sta/Elev= 30
       0 1951.36    14.8 1950.13    54.1 1941.42   108.2 1920.73   137.6 1914.44
   142.6 1912.31   186.8 1881.95   196.6 1876.62   364.8 1822.78   419.3 1798.31
     454 1793.37   505.1 1792.41   513.4 1791.77   520.1 1791.92   602.5 1792.48
   637.2 1795.56     657 1802.06   691.7 1820.34   736.2 1839.86   761.2 1845.87
   866.2 1864.22   971.1 1890.13   986.1 1894.84    1021 1911.62    1066 1919.35
    1086 1930.16    1096 1933.43    1146 1937.34  1320.8 1962.67  1385.8 1966.01
#Mann= 3 , 0 , 0
       0      .1       0   505.1    .045       0   520.1      .1       0
Bank Sta=505.1,520.1
XS Rating Curve= 0 ,0
Exp/Cntr=0.3,0.1

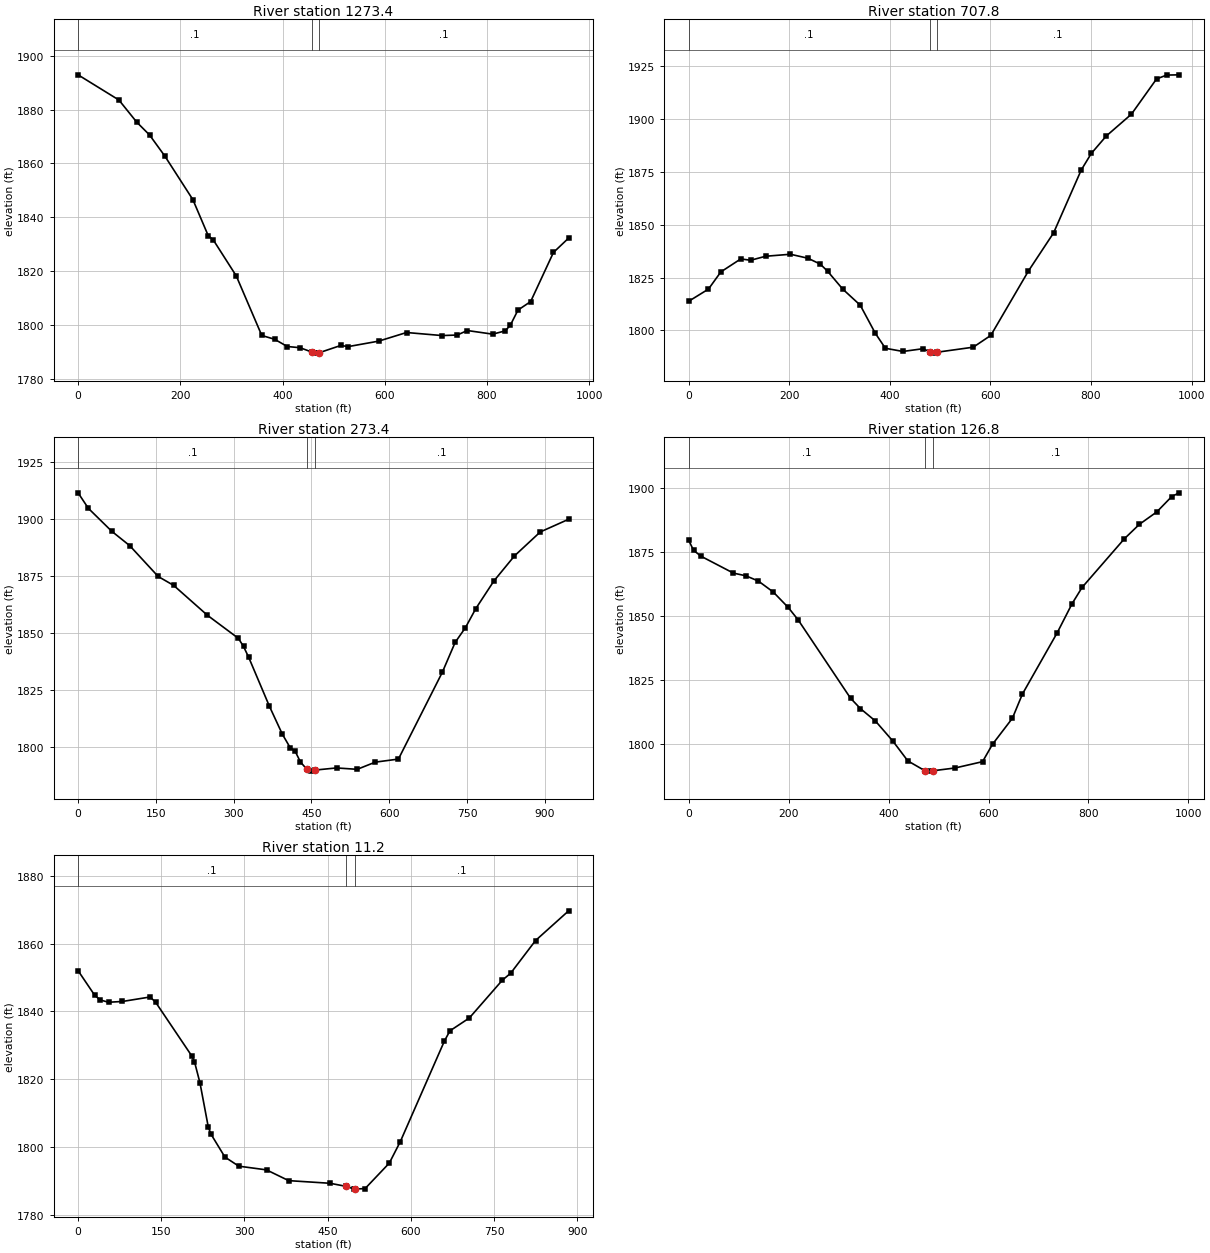
Type RM Length L Ch R = 1 ,1273.4  ,540,565.5,597
XS GIS Cut Line= 3
     1818976.492      232500.057     1818586.694      232247.938
     1818151.153      232011.681
#Sta/Elev= 30
       0 1892.92    79.9 1883.56   114.8 1875.33   139.8 1870.58   169.7 1862.74
   224.6 1846.54   254.6 1833.16   264.6 1831.54   309.5 1818.19   359.4 1796.06
   384.4 1794.66   409.3 1791.96   434.3 1791.51   456.7 1789.94   464.2  1789.5
   471.7 1789.65   513.8 1792.34   528.6 1791.93   588.1 1793.96   642.6 1797.16
     712 1796.03   741.7 1796.22   761.5  1797.9   811.1 1796.55   835.8 1797.78
   845.8 1799.93   860.6  1805.5   885.4 1808.66     930 1826.92   959.7 1832.26
#Mann= 3 , 0 , 0
       0      .1       0   456.7    .045       0   471.7      .1       0
Bank Sta=456.7,471.7
XS Rating Curve= 0 ,0
Exp/Cntr=0.3,0.1

Type RM Length L Ch R = 1 ,707.8   ,449,434.5,420.4
XS GIS Cut Line= 3
     1819087.272      232313.982     1818856.558      232128.035
     1818606.366      231496.963
#Sta/Elev= 30
       0 1813.79    39.5 1819.58    64.2 1827.72   103.7 1833.85   123.5 1833.22
   153.1 1835.11   202.5 1836.06   237.1 1834.18   261.8  1831.4   276.6 1827.96
   306.3  1819.6   341.2 1811.98   371.2 1798.68   391.2 1791.59   426.1 1790.08
     466 1791.38   479.3    1790     486 1789.29   494.3 1789.73   565.9  1792.1
   600.8 1797.68   675.7 1828.18   725.6 1846.17   780.5 1875.89   800.5 1883.73
   830.4 1892.01   880.3 1902.31   930.2 1918.96   950.2 1920.81   975.2 1920.93
#Mann= 3 , 0 , 0
       0      .1       0   479.3    .045       0   494.3      .1       0
Bank Sta=479.3,494.3
XS Rating Curve= 0 ,0
Exp/Cntr=0.3,0.1

Type RM Length L Ch R = 1 ,273.4   ,144.4,146.5,145.6
XS GIS Cut Line= 3
     1819485.845      231957.458     1819099.758      231728.895
     1818709.533       231420.69
#Sta/Elev= 30
       0 1911.52    19.9  1904.7    64.8 1894.68    99.7 1888.31   154.5  1874.8
   184.4 1870.88   249.3  1857.8   309.1 1847.66     319  1844.1     329 1839.33
   368.9 1817.87   393.8 1805.62   408.8 1799.74   418.8 1798.01   428.7 1793.42
   441.2 1790.16   448.7 1789.38   456.2 1789.83   498.4 1790.78   538.2 1790.17
     573 1793.32   617.7 1794.67   702.3 1832.75   727.1 1845.89     747 1852.38
   766.9 1860.71   801.7 1872.81   841.5 1883.85   891.2 1894.35   945.9 1899.92
#Mann= 3 , 0 , 0
       0      .1       0   441.2    .045       0   456.2      .1       0
Bank Sta=441.2,456.2
XS Rating Curve= 0 ,0
Exp/Cntr=0.3,0.1

Type RM Length L Ch R = 1 ,126.8   ,117,115.7,118
XS GIS Cut Line= 3
     1819555.028      231881.626      1819123.31      231568.512
     1818708.988      231397.723
#Sta/Elev= 30
       0 1879.75      10 1875.73    24.9 1873.42    89.7 1866.81   114.6 1865.76
   139.6  1863.7   169.5 1859.38   199.4 1853.34   219.3 1848.45     324 1817.79
   343.9  1813.7   373.8 1808.85   408.7 1800.99   438.6 1793.23   473.4 1789.31
   478.5 1789.22   488.4 1789.35   533.3 1790.46   588.1 1792.93     608 1799.74
   647.8 1809.94   667.8 1819.41   737.5 1843.46   767.3 1854.87   787.3 1861.23
   871.9 1880.29   901.8 1885.92   936.6 1890.78   966.5  1896.8   981.4 1898.27
#Mann= 3 , 0 , 0
       0      .1       0   473.4    .045       0   488.4      .1       0
Bank Sta=473.4,488.4
XS Rating Curve= 0 ,0
Exp/Cntr=0.3,0.1

Type RM Length L Ch R = 1 ,11.2    ,20.3,11.2,2
XS GIS Cut Line= 4
      1819580.33      231805.509     1819238.751      231512.953
     1819143.868      231454.442     1818829.173      231380.117
#Sta/Elev= 30
       0 1852.01      30 1844.76      40 1843.38      55 1842.71      80 1842.94
   129.9 1844.26   139.9  1842.7   204.9 1826.93   209.9 1825.21   219.9  1818.9
   234.9 1805.89   239.9  1803.8   264.8 1797.12   289.8 1794.44   339.8 1793.35
   379.8 1790.18   454.6  1789.4   483.9 1788.47   498.2 1787.68   498.9 1787.69
   517.6 1787.85   561.2 1795.34   581.1 1801.68   660.7 1831.33   670.6  1834.3
   705.5 1838.07   765.2 1849.23   780.1 1851.26   824.9 1860.88   884.6 1869.63
#Mann= 3 , 0 , 0
       0      .1       0   483.9    .045       0   498.9      .1       0
Bank Sta=483.9,498.9
XS Rating Curve= 0 ,0
Exp/Cntr=0.3,0.1

Chan Stop Cuts=-1
Use User Specified Reach Order=0